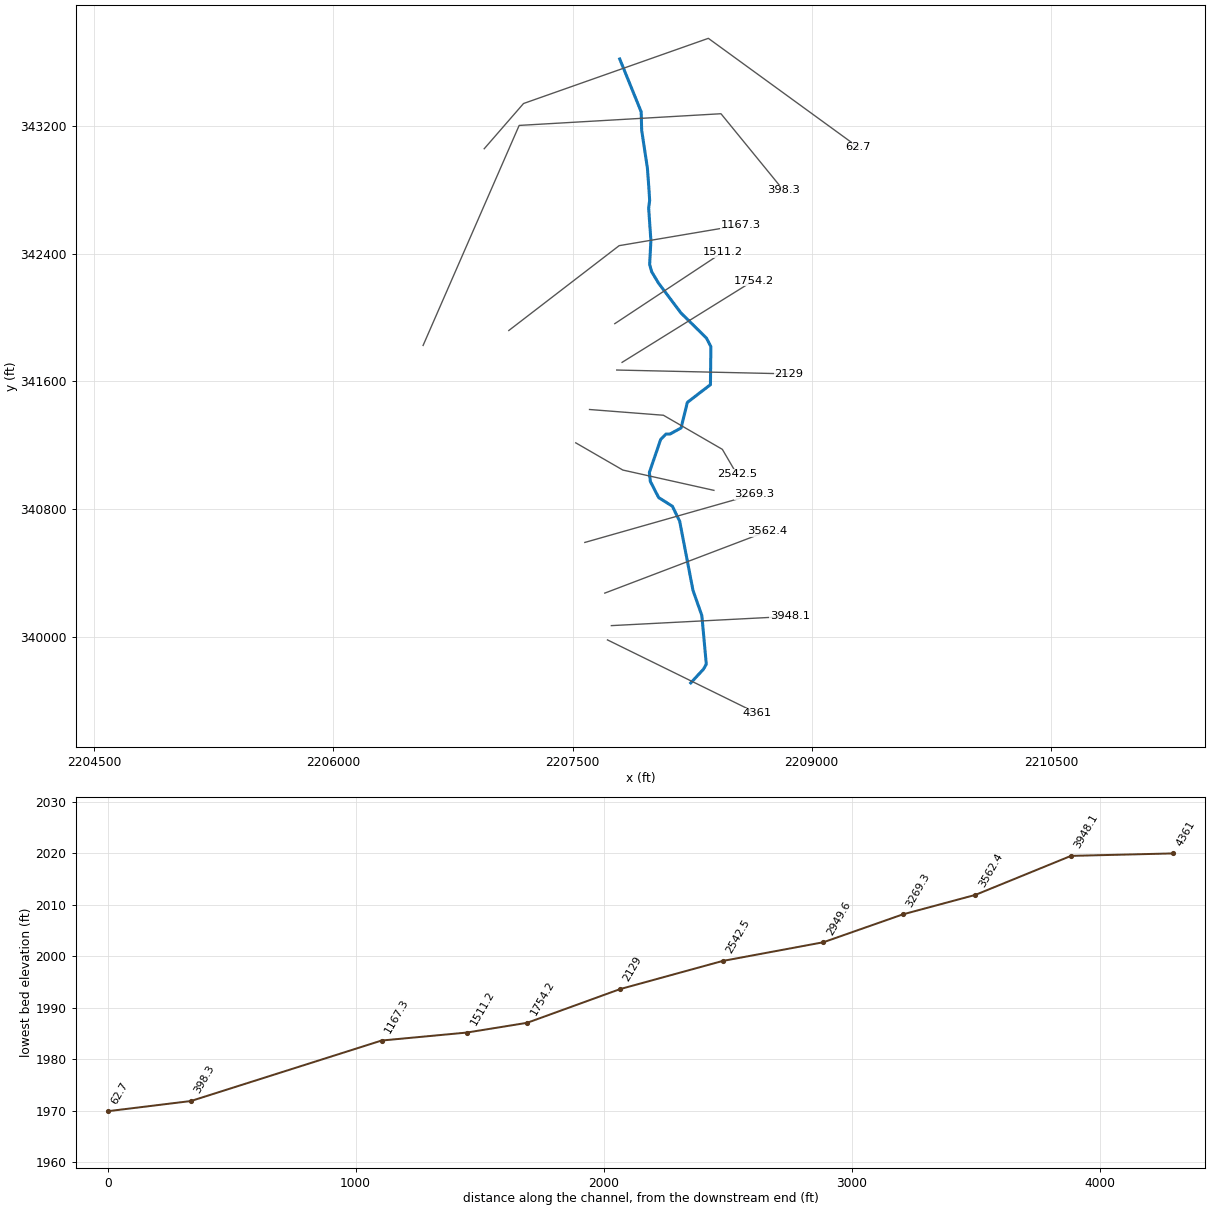
--- WileyRun.prj (project) ---

Proj Title=WileyRun
Current Plan=p01
Default Exp/Contr=0,0
English Units
Geom File=g01
Flow File=f01
Plan File=p01
BEGIN DESCRIPTION:
END DESCRIPTION:
DSS Export Rating Curves= 0
DSS Export Rating Curve Sorted= 0
DSS Export Volume Flow Curves= 0
DXF OffsetX= 0
DXF OffsetY= 0
DXF ScaleX= 0
DXF ScaleY= 0

--- WileyRun.p01 (plan) ---

Plan Title=Floodplain
Program Version=4.00
Geom File=g01
Flow File=f01
K Sum by GR=0
Std Step Tol=0.01
Critical Tol=0.01
Num of Std Step Trials=20
Max Error Tol=0.3
Flow Tol Ratio=0.001
Split Flow NTrial=30
Split Flow Tol=0.02
Split Flow Ratio=0.02
Log Output Level=0
Friction Slope Method=1
Unsteady Friction Slope Method=2
Unsteady Bridges Friction Slope Method=1
Global Log Level=0
CheckData=False
Run HTab=0
Run UNet=0
Run PostProcess=0
UNET Theta=0
UNET Theta Warmup=0
UNET ZTol=0
UNET ZSATol=0
UNET MxIter=0
UNET MaxInSteps=0
UNET DtIC=0
UNET DtMin=0
UNET MaxCRTS=0
UNET WFStab=0
UNET SFStab=0
UNET WFX=0
UNET SFX=0
UNET DSS MLevel=0
UNET DZMax Abort=0
UNET Convert EG Bridges=0
UNET Use Existing IB Tables=0
UNET Froude Limit=0
UNET Froude Power=0
Write IC File=0
Echo Input=False
Echo Output=False
Write Detailed=0

--- WileyRun.f01 (steady flow) ---

Flow Title=NFF Regression Equation
Program Version=4.00
Number of Profiles=1
Profile Names=P100yr
River Rch & RM=WileyRun,Main      ,4361
545.8678
River Rch & RM=WileyRun,Main      ,2542.5
558.0776
River Rch & RM=WileyRun,Main      ,2129
669.0887
River Rch & RM=WileyRun,Main      ,1754.2
812.8129
River Rch & RM=WileyRun,Main      ,62.7
822.0363
Boundary for River Rch & Prof#=WileyRun,Main      ,1
Up Type=0
Dn Type=3
Dn Slope=0.009714

--- WileyRun.g01 (geometry) ---

Geom Title=USGS 10m DEM
Program Version=4.10

River Reach=WileyRun        ,Main
Reach XY= 30
     2208241.162      339709.932     2208320.396      339795.367
     2208338.619      339826.785     2208310.657      340132.491
     2208255.224       340289.62     2208171.785      340722.538
     2208125.914      340816.794     2208039.788      340871.273
     2207987.828      340972.265     2207981.544        341028.4
     2208052.621      341235.619     2208086.036      341269.307
     2208111.408      341269.307      2208180.53        341307.4
     2208219.638      341467.365       2208364.6      341578.682
     2208367.368      341816.805     2208339.479      341870.703
     2208179.273      342028.359     2208038.037      342216.182
      2207995.85      342286.495      2207983.35      342331.807
     2207991.162      342481.807       2207977.1      342684.932
      2207983.35       342733.37     2207978.662       342808.37
     2207969.287      342934.932     2207933.349      343172.432
     2207930.224      343288.057     2207795.597      343619.101

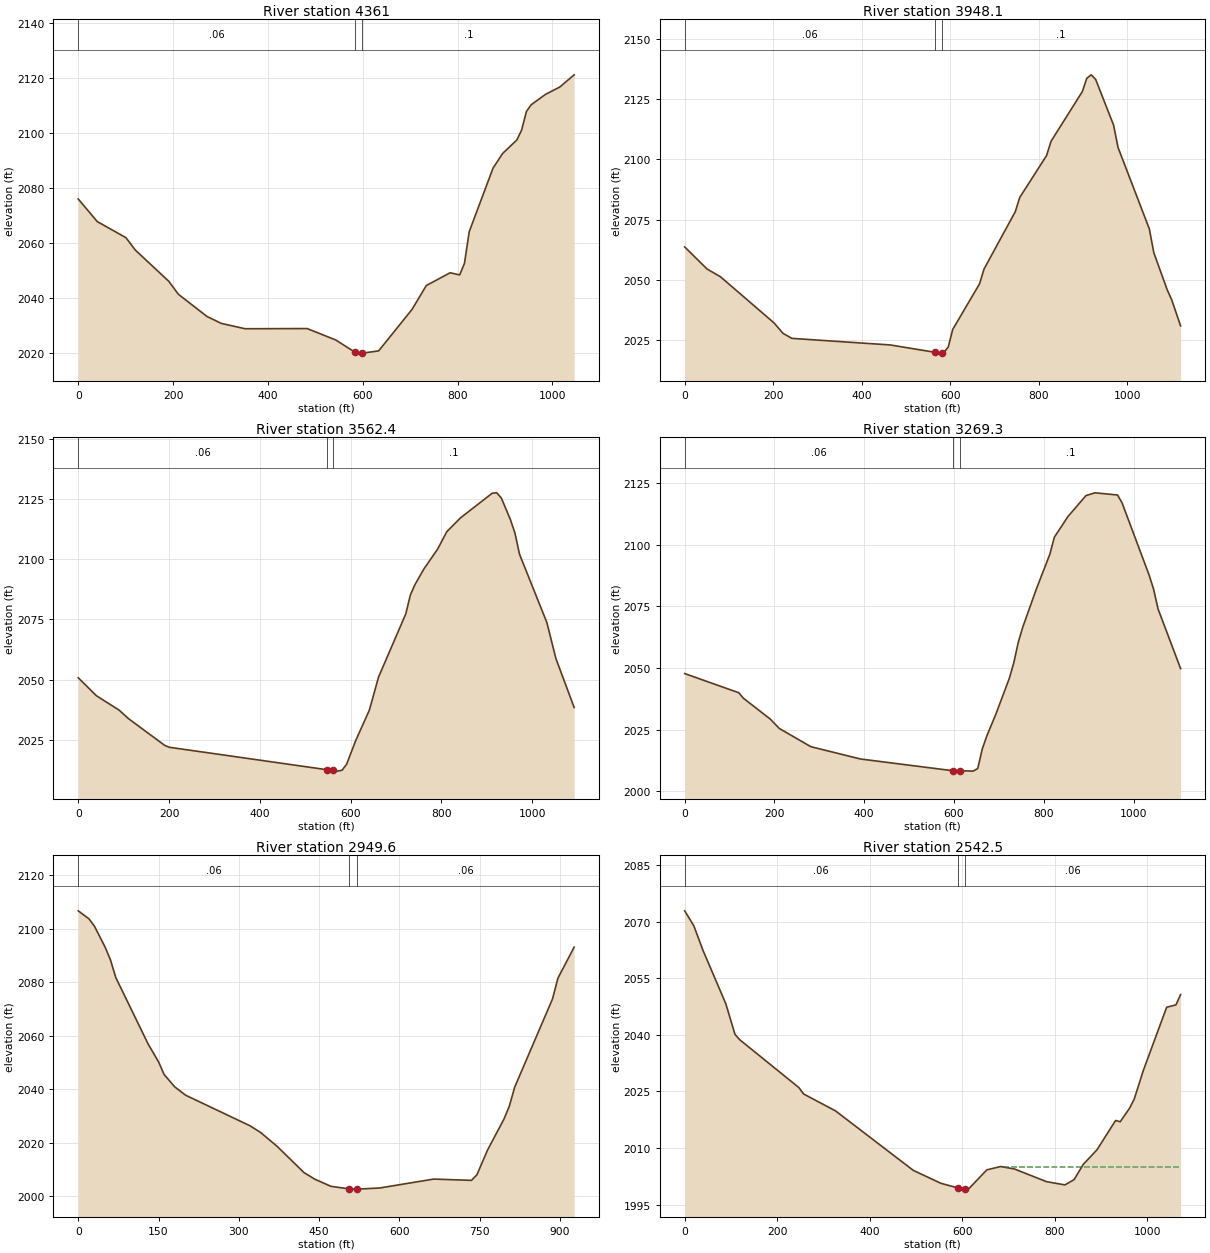
Type RM Length L Ch R = 1 ,4361    ,401.4,413.1,424.8
XS GIS Cut Line= 2
     2207718.753      339979.447     2208657.858      339519.092
#Sta/Elev= 30
       0 2076.07    40.2 2067.84   100.6 2061.99   120.7 2057.42   191.1  2046.1
   211.2  2041.4   271.5 2033.32   301.7 2030.79     352 2028.84   482.7 2028.91
     543 2024.77   584.5 2020.22   593.3 2019.97   599.5 2019.97   633.6 2020.78
     704 2035.88   734.1 2044.56   784.4 2049.21   804.5 2048.43   814.6 2052.65
   824.6 2064.15   874.9 2087.31     895  2092.6   925.2 2097.57   935.2 2101.17
   945.3 2107.92   955.4 2110.36   985.5 2114.13  1015.7 2116.81  1045.9 2121.24
#Mann= 3 , 0 , 0
       0     .06       0   584.5    .045       0   599.5      .1       0
Bank Sta=584.5,599.5
XS Rating Curve= 0 ,0
Exp/Cntr=0.3,0.1

Type RM Length L Ch R = 1 ,3948.1  ,378.5,385.5,392.6
XS GIS Cut Line= 2
     2207743.121      340068.895     2208862.167      340126.857
#Sta/Elev= 30
       0 2063.62    50.5 2054.46    80.8 2051.23   201.9 2032.05   222.1 2027.73
   242.3 2025.62   464.4 2022.89   565.7 2019.83   575.4 2019.49   580.7 2019.61
   585.5 2019.71   595.6 2022.05   605.7 2029.36   666.3 2048.29   676.4 2054.43
     747 2078.25   757.1 2084.17   817.7 2101.57   827.8 2107.51   898.5 2128.17
   908.6  2133.7   918.6 2135.13   928.7  2133.2   969.1 2114.26   979.2 2104.94
  1049.9 2071.12    1060 2061.24  1090.3 2045.79  1100.4 2041.68  1120.6 2030.79
#Mann= 3 , 0 , 0
       0     .06       0   565.7    .045       0   580.7      .1       0
Bank Sta=565.7,580.7
XS Rating Curve= 0 ,0
Exp/Cntr=0.3,0.1

Type RM Length L Ch R = 1 ,3562.4  ,295.1,293.1,291.2
XS GIS Cut Line= 2
     2207701.961      340272.599     2208723.084      340660.708
#Sta/Elev= 30
       0 2050.76    40.1 2043.28    90.2 2037.27   110.2 2033.84   190.4 2022.64
   200.4 2021.85   547.3 2012.52   562.3 2012.28   571.2 2011.92   581.3 2012.32
   591.3 2014.82   611.3 2024.66   641.4 2037.31   661.4 2050.97   721.6 2077.34
   731.6 2085.17   741.6 2089.44   761.7 2096.08   791.7 2104.26   811.8 2111.49
   841.8 2117.21     912 2127.52     922 2127.67     932 2125.52   952.1 2116.48
   962.1 2110.87   972.1 2102.12  1032.3 2073.72  1052.3  2058.7  1092.4  2038.4
#Mann= 3 , 0 , 0
       0     .06       0   547.3    .045       0   562.3      .1       0
Bank Sta=547.3,562.3
XS Rating Curve= 0 ,0
Exp/Cntr=0.3,0.1

Type RM Length L Ch R = 1 ,3269.3  ,331.5,319.7,307.8
XS GIS Cut Line= 2
     2207576.673      340590.065     2208639.489      340892.081
#Sta/Elev= 30
       0 2047.71   120.5 2039.93   130.6 2037.74   190.8 2029.22   210.9 2025.43
   281.2 2018.04   391.7 2013.05   598.4 2008.27   613.4 2008.29   642.8 2008.13
   652.9  2009.2   662.9 2017.04     673 2022.34   693.1 2031.15   723.2 2045.72
   733.2 2052.06   743.3 2060.46   753.3 2066.58   783.5    2082   813.6 2096.14
   823.6 2103.02   853.8 2111.38     894  2119.9     914 2121.03   964.3 2120.15
   974.3 2117.03  1034.6 2087.74  1044.6 2082.01  1054.7 2073.89  1104.9 2049.72
#Mann= 3 , 0 , 0
       0     .06       0   598.4    .045       0   613.4      .1       0
Bank Sta=598.4,613.4
XS Rating Curve= 0 ,0
Exp/Cntr=0.3,0.1

Type RM Length L Ch R = 1 ,2949.6  ,414.1,407.1,400.1
XS GIS Cut Line= 3
     2207519.839      341214.117     2207815.148      341043.654
     2208386.558      340916.407
#Sta/Elev= 30
       0 2106.61    20.1 2103.62    30.1 2100.96    50.1 2093.12    60.2 2088.34
    70.2  2081.7   130.4 2056.98   150.4 2050.11   160.5  2045.5   180.5 2040.87
   200.6 2037.79   320.9 2026.38     341 2023.83   371.3 2018.75   421.7 2008.92
   441.9 2006.44   472.2 2003.77   506.5 2002.82   521.5 2002.73     563 2003.15
     664 2006.48   734.6    2006   744.7 2008.05   764.9 2017.43   795.2 2028.83
   805.3  2033.7   815.4 2040.82     886 2073.74   896.1 2081.48   926.4 2093.05
#Mann= 3 , 0 , 0
       0     .06       0   506.5    .045       0   521.5     .06       0
Bank Sta=506.5,521.5
XS Rating Curve= 0 ,0
Exp/Cntr=0.3,0.1

Type RM Length L Ch R = 1 ,2542.5  ,401,413.3,425.7
XS GIS Cut Line= 4
     2207606.271      341422.994     2208069.641      341386.981
     2208439.378      341173.302     2208530.611      341017.244
#Sta/Elev= 30
       0 2072.88    19.8 2068.91    39.6  2062.4      89 2048.24   108.8 2040.13
   118.7 2038.74   247.2 2025.99   257.1 2024.33   326.3 2019.83   494.6 2004.05
   554.2 2000.63   590.5 1999.42   605.5  1999.1   613.7 1999.09   653.5  2004.2
   683.2 2005.08     713 2004.44   782.6 2001.07   822.3 2000.21   842.2  2001.6
     862 2005.64   891.8 2009.53     932 2017.29     942 2016.96   962.1 2020.53
   972.2 2022.94   992.2 2030.64  1042.4 2047.31  1062.5 2047.95  1072.6 2050.69
#Mann= 3 , 0 , 0
       0     .06       0   590.5    .045       0   605.5     .06       0
#XS Ineff= 2 , 0
                           689.1         2005.08
Permanent Ineff=
       F       F
Bank Sta=590.5,605.5
XS Rating Curve= 0 ,0
Exp/Cntr=0.3,0.1

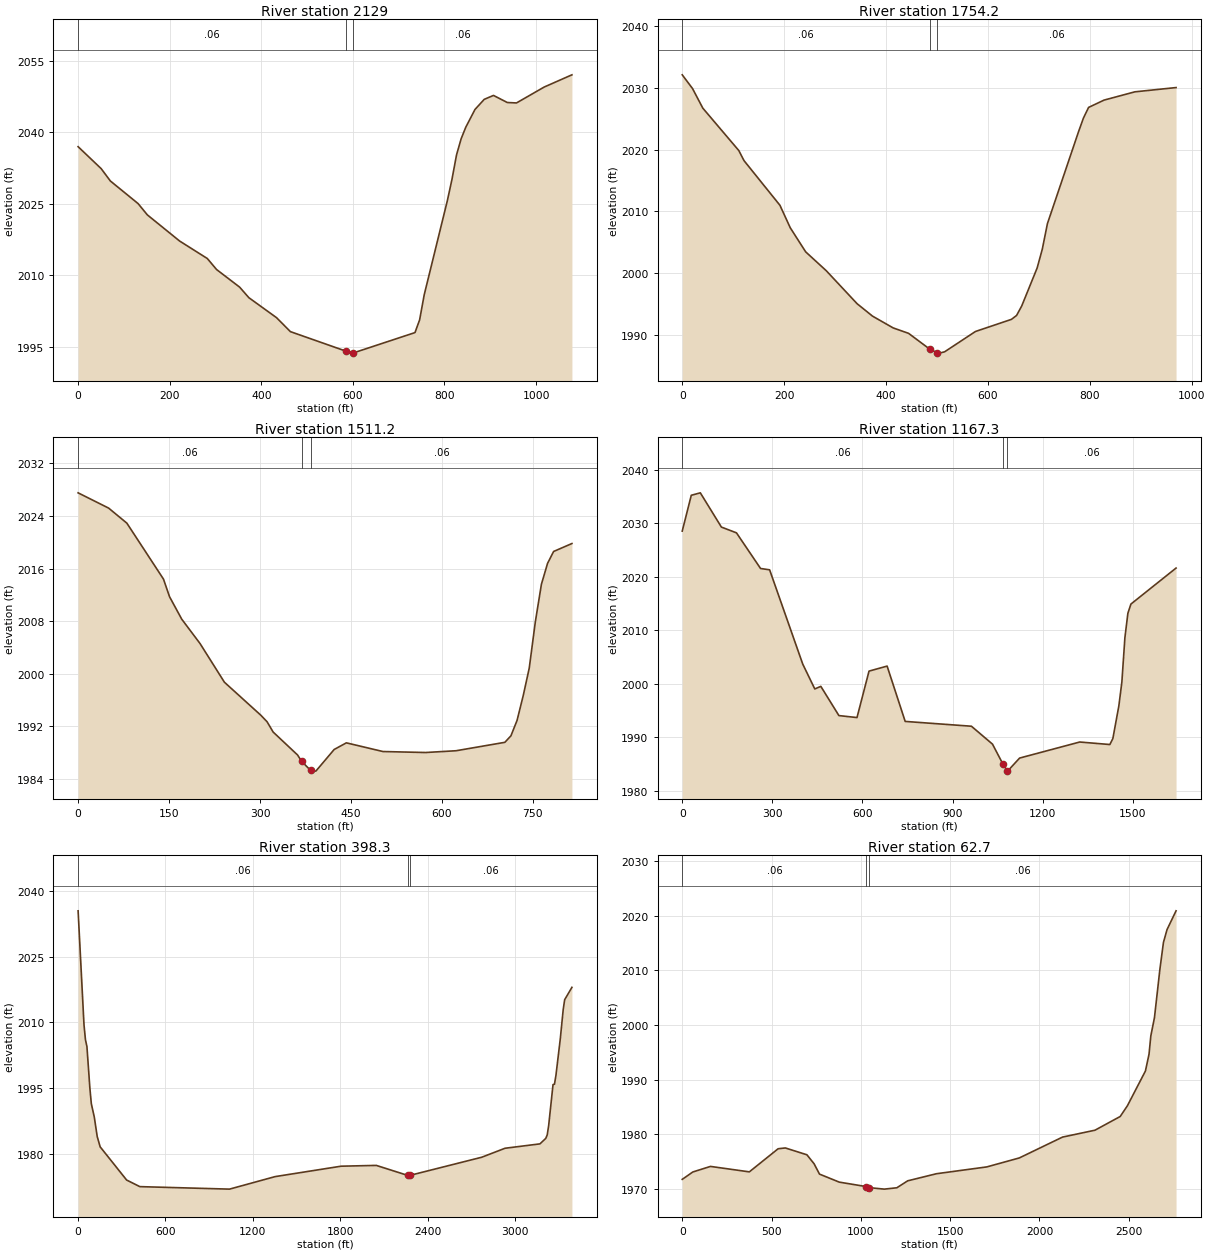
Type RM Length L Ch R = 1 ,2129    ,361.6,374.7,387.8
XS GIS Cut Line= 2
     2207776.734      341670.285     2208854.731      341646.276
#Sta/Elev= 30
       0 2036.95    50.4 2032.34    70.5 2029.75     131 2025.01   151.2 2022.64
   221.7 2017.15   282.2 2013.48   302.3 2011.18   352.7 2007.48   372.9 2005.26
   433.3 2001.07   463.6 1998.14   584.7 1994.05   594.6 1993.63   599.7 1993.63
   735.6 1997.94   745.7  2000.6   755.8 2005.89   806.2 2025.59   816.3 2030.06
   826.3 2035.22   836.4 2038.61   846.5 2041.03   866.6 2044.76   886.8 2046.88
     907 2047.71   937.2 2046.22   957.3 2046.13  1017.8 2049.47  1078.3 2052.03
#Mann= 3 , 0 , 0
       0     .06       0   584.7    .045       0   599.7     .06       0
Bank Sta=584.7,599.7
XS Rating Curve= 0 ,0
Exp/Cntr=0.3,0.1

Type RM Length L Ch R = 1 ,1754.2  ,242.4,243.1,243.8
XS GIS Cut Line= 2
     2207810.346      341718.303     2208633.849      342229.691
#Sta/Elev= 30
       0  2032.1    20.2 2029.88    40.4 2026.71   111.1 2019.85   121.2 2018.23
   191.8    2011     212 2007.37   242.3 2003.47   282.7 2000.42   343.3 1995.08
   373.6 1993.07     414 1991.17   444.3 1990.29   485.6 1987.75   500.6 1987.15
   504.9 1987.09     515  1987.3   575.6 1990.59   646.2 1992.55   656.3 1993.18
   666.4 1994.71   696.7 2000.86   706.8  2003.9   716.9 2008.04   777.5 2022.79
   787.6 2025.11   797.7 2026.83     828 2028.01   888.6 2029.35   969.4 2030.04
#Mann= 3 , 0 , 0
       0     .06       0   485.6    .045       0   500.6     .06       0
Bank Sta=485.6,500.6
XS Rating Curve= 0 ,0
Exp/Cntr=0.3,0.1

Type RM Length L Ch R = 1 ,1511.2  ,353.3,343.8,334.2
XS GIS Cut Line= 2
     2207764.729      341960.792      2208444.18      342409.758
#Sta/Elev= 30
       0 2027.52    50.3  2025.2    80.4 2022.91   140.8  2014.4   150.8 2011.72
   170.9 2008.31   201.1  2004.6   241.3 1998.72   301.6 1993.68   311.7  1992.7
   321.7 1991.14     362 1987.65   368.6 1986.69   383.6  1985.3   392.1  1985.2
   422.3 1988.49   442.4  1989.5   502.7 1988.18   573.1 1988.03   623.4  1988.3
   703.8 1989.58   713.8 1990.57   723.9 1992.91     734 1996.65     744 2000.86
   754.1 2007.93   764.1 2013.62   774.2 2016.79   784.2  2018.6   814.4 2019.81
#Mann= 3 , 0 , 0
       0     .06       0   368.6    .045       0   383.6     .06       0
Bank Sta=368.6,383.6
XS Rating Curve= 0 ,0
Exp/Cntr=0.3,0.1

Type RM Length L Ch R = 1 ,1167.3  ,771.6,769.1,766.6
XS GIS Cut Line= 3
     2207099.969      341917.889     2207792.196      342449.586
     2208552.935      342578.023
#Sta/Elev= 30
       0 2028.51    30.1  2035.2    60.2 2035.66   130.4 2029.26   180.6 2028.18
   260.8 2021.52     291 2021.27   401.3 2003.65   441.4 1999.01   461.5 1999.49
   521.7 1994.03   581.9 1993.66     622 2002.34   682.2 2003.28   742.4 1992.94
     963 1992.04  1033.2 1988.69  1067.1 1985.05  1082.1 1983.73  1083.3 1983.65
  1123.4 1986.09  1323.7 1989.09  1423.9 1988.62    1434 1989.75    1454 1995.88
    1464 2000.34    1474 2008.57    1484 2013.16  1494.1 2014.87  1644.4  2021.6
#Mann= 3 , 0 , 0
       0     .06       0  1067.1    .045       0  1082.1     .06       0
Bank Sta=1067.1,1082.1
XS Rating Curve= 0 ,0
Exp/Cntr=0.3,0.1

Type RM Length L Ch R = 1 ,398.3   ,329.2,335.6,342
XS GIS Cut Line= 4
     2206562.348      341824.286     2207164.908       343202.87
     2208430.675      343276.137     2208822.431      342796.756
#Sta/Elev= 30
       0  2035.5    40.4 2009.48    50.5 2006.04    60.6 2004.49    80.8    1995
    90.9 1991.41   111.1 1988.39   131.3 1983.92   151.5 1981.57   333.2 1973.99
   424.1 1972.48    1040 1971.91  1353.1 1974.77  1806.4 1977.15  2047.9 1977.33
  2264.7 1975.04  2279.7 1975.06  2772.4  1979.2  2932.2 1981.25  3171.8 1982.25
  3211.8  1983.5  3221.8 1984.29  3231.7 1986.42  3261.7 1995.79  3271.7 1995.89
  3281.7 1997.91  3311.6 2006.24  3331.6 2012.94  3341.6 2015.19  3391.5 2018.02
#Mann= 3 , 0 , 0
       0     .06       0  2264.7    .045       0  2279.7     .06       0
#XS Ineff= 2 , 0
         2024.63 1977.24
Permanent Ineff=
       F       F
Bank Sta=2264.7,2279.7
XS Rating Curve= 0 ,0
Exp/Cntr=0.3,0.1

Type RM Length L Ch R = 1 ,62.7    ,62.7,62.7,62.7
XS GIS Cut Line= 4
     2206945.795      343056.795     2207192.276      343340.141
     2208351.497      343748.503     2209290.071      343066.801
#Sta/Elev= 30
       0 1971.72    59.3 1973.07   158.1 1974.09   375.6 1973.09   536.7 1977.32
     577 1977.47   697.9 1976.22   738.2 1974.57   768.4 1972.68   879.3 1971.21
  1031.3 1970.39  1046.3  1970.2  1131.1 1969.93  1201.6 1970.18  1262.1 1971.45
  1423.3 1972.75  1705.5    1974    1887 1975.64  2129.1 1979.46  2310.7 1980.72
  2451.9 1983.23  2492.3  1985.2  2593.1 1991.56  2613.3 1994.64  2623.4    1998
  2643.6 2001.31  2673.8  2010.1    2694 2015.11  2714.2 2017.46  2764.6 2020.89
#Mann= 3 , 0 , 0
       0     .06       0  1031.3    .045       0  1046.3     .06       0
Bank Sta=1031.3,1046.3
XS Rating Curve= 0 ,0
Exp/Cntr=0.3,0.1

Chan Stop Cuts=-1
Use User Specified Reach Order=0
Composite Channel Slope=5